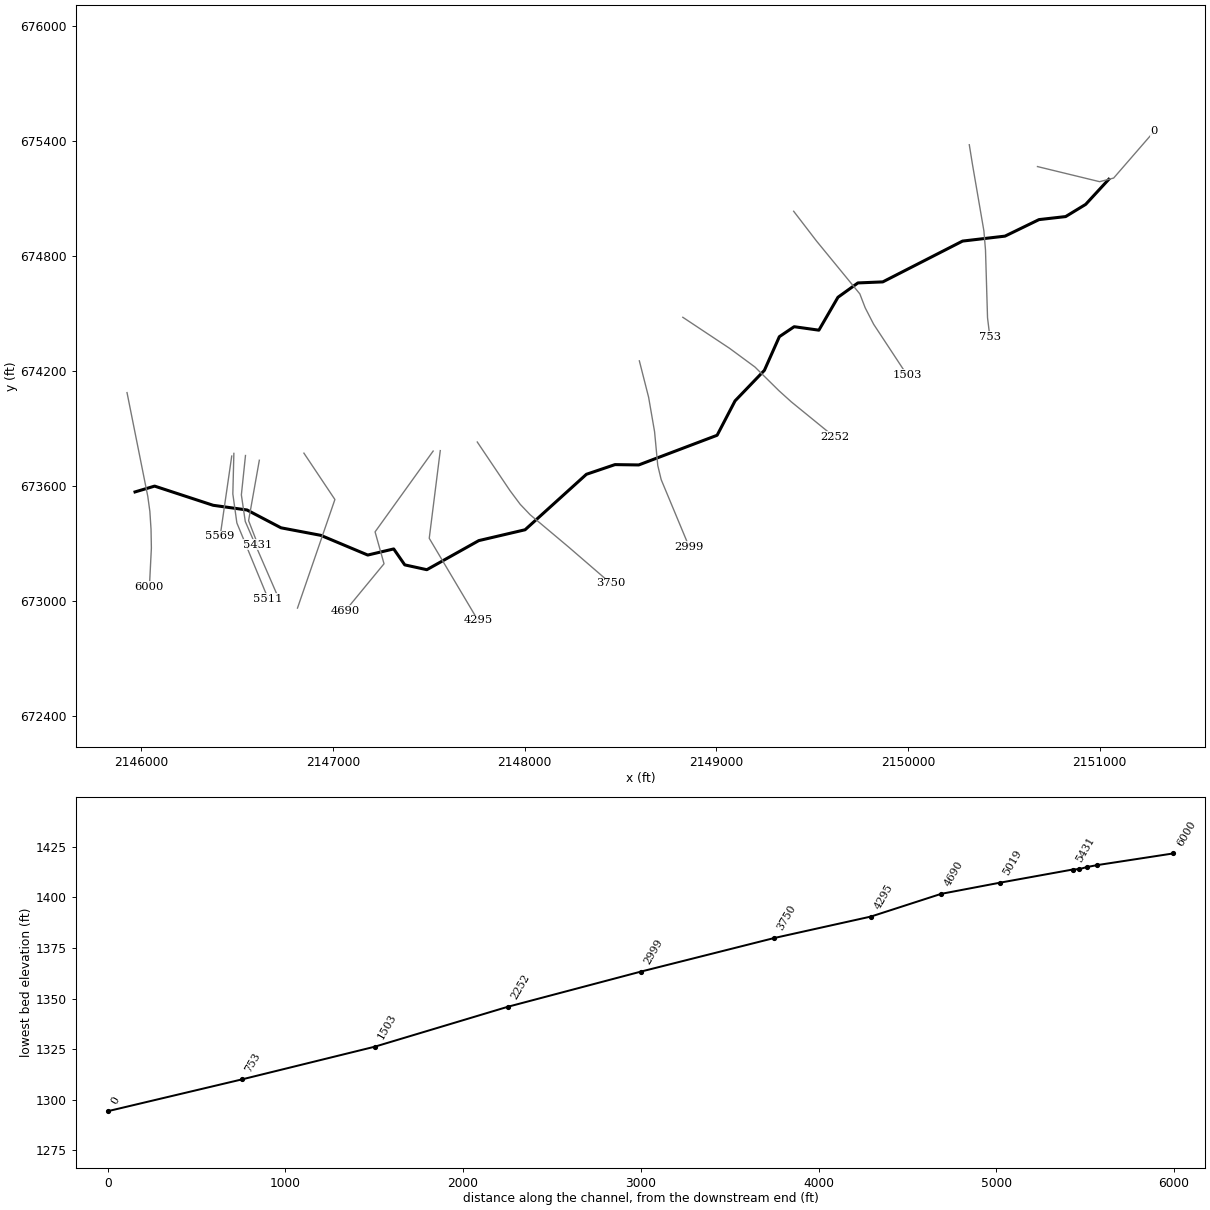
--- STFORK.prj (project) ---

Proj Title=STFORK
Current Plan=p01
Default Exp/Contr=0,0
English Units
Geom File=g01
Flow File=f01
Plan File=p01
BEGIN DESCRIPTION:
---------- MODELED AS PART OF WVEMD CTP PROGRAM, 2023----------
Stream Name: Straight Fork
Flood Zone:  AFH
Upshur County, WV
HEC-RAS Version: RAS 6.3
Vertical Datum: NAVD88
Projection: NAD 1983 StatePlane West Virginia S FIPS 4702 (US Feet)
Terrain: 1-meter LIDAR (FEMA Region III 3DEP collected 2016-2018)
Land Use: 2019 NLCD
Hydrologic Method:
WV SIR2010-5033 regression equations
Additional Model Notes:
KWSE with WFORKRV and WHITECMPFK to fix tie-in issues. Leveraged XS
END DESCRIPTION:
DSS Export Rating Curves= 0
DSS Export Rating Curve Sorted= 0
DSS Export Volume Flow Curves= 0
DXF OffsetX= 0
DXF OffsetY= 0
DXF ScaleX= 0
DXF ScaleY= 0

--- STFORK.p01 (plan) ---

Plan Title=Floodplain
Program Version=6.30
Short Identifier=Floodplain
Geom File=g01
Flow File=f01
Subcritical Flow
K Sum by GR= 0
Std Step Tol= 0.01
Critical Tol= 0.01
Num of Std Step Trials= 20
Max Error Tol= 0.3
Flow Tol Ratio= 0.001
Split Flow NTrial= 30
Split Flow Tol= 0.02
Split Flow Ratio= 0.02
Log Output Level= 0
Friction Slope Method= 1
Unsteady Friction Slope Method= 2
Unsteady Bridges Friction Slope Method= 1
Parabolic Critical Depth
Global Vel Dist= 0 , 0 , 0
Global Log Level= 0
CheckData=True
Encroach Param=-1 ,0,0, 0
Mapping Interval=1HOUR
Computation Time Step Use Courant=        0
Computation Time Step Use Time Series=    0
Computation Time Step Count To Double=0
Computation Time Step Max Doubling=0
Computation Time Step Max Halving=0
Computation Time Step Residence Courant=0
Run HTab= 0
Run UNet= 0
Run Sediment= 0
Run PostProcess= 0
Run WQNet= 0
Run RASMapper= 0
UNET Theta= 0
UNET Theta Warmup= 0
UNET ZTol= 0
UNET ZSATol= 0
UNET MxIter= 0
UNET Max Iter WO Improvement= 0
UNET MaxInSteps= 0
UNET DtIC= 0
UNET DtMin= 0
UNET MaxCRTS= 0
UNET WFStab= 0
UNET SFStab= 0
UNET WFX= 1
UNET SFX= 1
UNET Gravity=32.17405
UNET 1D Methodology=Finite Difference
UNET DSS MLevel= 1
UNET Pardiso=0
UNET DZMax Abort= 0
UNET Use Existing IB Tables= 0
UNET Froude Reduction=False
UNET Froude Limit= 0
UNET Froude Power= 0
UNET D1 Cores= 0
UNET WindReference=Eulerian
UNET WindDragFormulation=Hsu (1988)
UNET D2 Coriolis=0
UNET D2 Cores= 0
UNET D2 Theta= 1
UNET D2 Theta Warmup= 1
UNET D2 Z Tol= 0.01
UNET D2 Volume Tol= 0.01
UNET D2 Max Iterations= 20
UNET D2 Equation= 0
UNET D2 RampUpFraction=0.1
UNET D2 TimeSlices= 1
UNET D2 Turbulence Formulation=Non-Conservative (original)
UNET D2 Eddy Viscosity=0.3
UNET D2 Transverse Eddy Viscosity=0.1
UNET D2 Smagorinsky Mixing=0
UNET D2 BCVolumeCheck=0
UNET D2 Cores=0
UNET D2 SolverType=PARDISO (Direct)
UNET D2 Minimum Iterations= 3
UNET D2 Maximum Iterations= 30
UNET D2 Restart Number= 10
UNET D2 Relaxation Coeff=1.3
UNET D2 SOR Precondition Iterations= 10
UNET D2 ILUT Maximum Fill= 8
UNET D2 ILUT Tolerance=1E-08
UNET D2 Convergence Tolerance=0.00001
UNET D1D2 MaxIter= 0
UNET D1D2 ZTol=0.01
UNET D1D2 QTol=0.1
UNET D1D2 MinQTol=1
Write IC File= 0
Write IC File at Fixed DateTime=0
Write IC File at Sim End=0
Echo Input=False
Echo Parameters=False
Echo Output=False
Write Detailed= 0
HDF Write Warmup=0
HDF Write Time Slices=0
HDF Flush=0
HDF Compression= 1
HDF Chunk Size= 1
HDF Spatial Parts= 1
HDF Use Max Rows=0
HDF Fixed Rows= 1
Calibration Method= 0
Calibration Iterations= 20
Calibration Max Change=0.05
Calibration Tolerance=0.2
Calibration Maximum=1.5
Calibration Minimum=0.5
Calibration Optimization Method= 1
WQ AD Non Conservative
WQ ULTIMATE=-1
WQ Max Comp Step=1HOUR
WQ Output Interval=15MIN
WQ Output Selected Increments= 0
WQ Output face flow=0
WQ Output face velocity=0
WQ Output face area=0
WQ Output face dispersion=0
WQ Output cell volume=0
WQ Output cell surface area=0
WQ Output cell continuity=0
WQ Output cumulative cell continuity=0
WQ Output face conc=0
WQ Output face dconc_dx=0
WQ Output face courant=0
WQ Output face peclet=0
WQ Output face adv mass=0
WQ Output face disp mass=0
WQ Output cell mass=0
WQ Output cell source sink temp=0
WQ Output nsm pathways=0
WQ Output nsm derived pathways=0
WQ Create Restart=0
WQ Fixed Restart=0
WQ System Summary=0
WQ Write To DSS=0
Sorting and Armoring Iterations= 10
XS Update Threshold= 0.02
Bed Roughness Predictor= 0
Hydraulics Update Threshold= 0.02
Energy Slope Method= 1
Volume Change Method= 1
Sediment Retention Method= 0
Sediment TS Multiplier= 1
Warm Up Method= 0
XS Weighting Method= 0
Number of US Weighted Cross Sections= 1
Number of DS Weighted Cross Sections= 1
Upstream XS Weight=0
Main XS Weight=1
Downstream XS Weight=0
Number of DS XS's Weighted with US Boundary= 1
Upstream Boundary Weight= 1
Weight of XSs Associated with US Boundary= 0
Number of US XS's Weighted with DS Boundary= 1
Downstream Boundary Weight= 0.5
Weight of XSs Associated with DS Boundary= 0.5
Percentile Method= 0
Sediment Output Level= 3
Mass or Volume Output= 0
Output Increment Type= 1
Profile and TS Output Increment= 1
Transport Output Increment 1
XS Output Flag= 0
XS Output Increment= 10
Read HDF5 Sediment Hotstart= 0
Sediment Hotstart Type= 0
Write Gradation File= 0
Read Gradation Hotstart= 0
Write HDF5 File= 1
Write Binary Output= 1
Write DSS Sediment File= 0
DSS Sediment Output Type= 1
SV Curve= 0
Specific Gage Flag= 0
Subcell Erosion Methods= 0
Subcell Deposition Methods= 0
Advection Scheme= 1
Matrix Solver= 0
Implicit Weighting Factor= 1
Maximum Outer Loop Convergence Iterations= 5
Convergence Maximum Absolute= 0.001
Convergence RMSE= 0.0001
Grain Fractions Max Abs Error= 0.001
Max Subgrid Regions= 1
Max Subgrid Length Scale= 3.402823E+38
Initial Layer Thickness= 3.402823E+38
Min Layer Thickness= 3.402823E+38
Max Layer Thickness= 3.402823E+38
Number of Layers= 5

--- STFORK.f01 (steady flow) ---

Flow Title=Flows
Program Version=6.20
Number of Profiles= 1
Profile Names=01pct
River Rch & RM=STFORK,Main            ,6000
     653
River Rch & RM=STFORK,Main            ,4690
     873
River Rch & RM=STFORK,Main            ,0
    2060
Boundary for River Rch & Prof#=STFORK,Main            , 1
Up Type= 0
Dn Type= 1
Dn Known WS=1299.2
DSS Import GetInterval= 0
DSS Import GetPeak= 0
DSS Import FillOption= 0

--- STFORK.g01 (geometry) ---

Geom Title=Geometry
Program Version=6.31

River Reach=STFORK          ,Main
Reach XY= 30
     2145966.443673566.7800000012146068.66100001673597.170000017
2146374.08400001673497.0699999932146550.79000005673472.575000018
2146728.26899998673379.5430000132146935.88099998673340.253000006
2147180.83700004      673237.4342147316.30700001673269.313000008
2147373.85500002673186.1529999972147489.09299999673160.998999998
     2147760.176673312.7810000032148001.78400001673369.384000018
2148321.80100003673658.8390000022148470.94999999673709.375000015
2148594.85900004 673707.630000012149003.87300003673862.502000004
2149097.44800003674041.9260000142149250.48900001674201.233999997
2149328.61200002674376.938000008     2149405.876674428.963000014
2149534.85000002674410.8490000072149634.37800002674582.518999994
2149738.48400004674657.3790000082149868.28800003674662.788000017
2150284.59900004674875.751000002     2150506.119674901.591000006
2150683.42600003674987.7839999942150822.50100002675003.608999997
2150926.98000003675067.2800000162151047.59157684675198.062639669

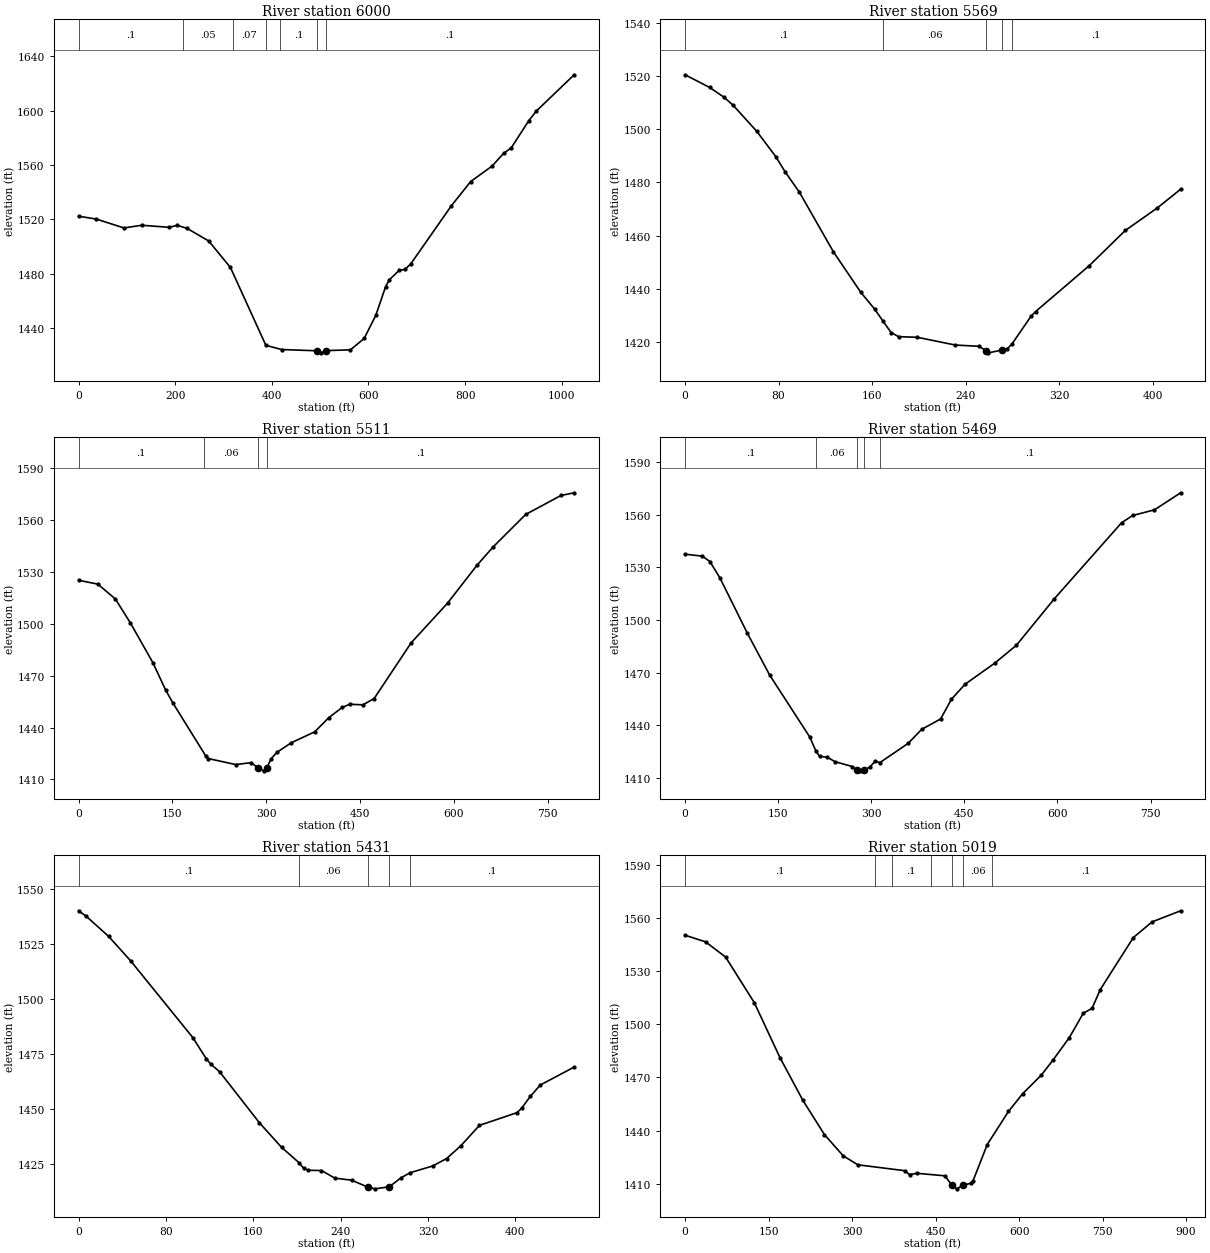
Type RM Length L Ch R = 1 ,6000    ,429.5,429.5,429.5
XS GIS Cut Line= 6
2145924.65163125674085.0590435122146033.10023326673543.237620592
2146043.87777075673464.7039850062146049.93648568673372.056860596
2146051.75505158673273.7086320822146041.46471784673071.247750923
#Sta/Elev= 30
       0 1522.36    36.6 1520.25    93.8 1513.72   130.5 1515.69   187.7 1514.19
     204 1515.64   224.4 1513.43   269.3  1504.1   314.2 1484.64   387.6 1427.29
   420.2 1424.19   493.5 1423.27   501.7 1421.76   512.6 1423.41   562.7 1423.96
     591 1432.32   615.2  1449.4   635.4 1470.45   643.4 1475.64   663.4 1482.42
   675.5 1483.23   687.5 1487.23   771.6 1530.06   811.6  1547.9   855.6 1559.19
   879.6 1568.57   895.6 1572.71   931.7 1592.63   947.7 1599.88  1025.8  1626.5
#Mann= 7 ,-1,0
       0      .1       0  215.55     .05       0  319.44     .07       0
  387.14     .06       0  417.14      .1       0   493.5    .045       0
   512.6      .1       0
Bank Sta=493.5,512.6
XS Rating Curve= 0 ,0
Exp/Cntr(USF)=0,0
Exp/Cntr=0.3,0.1

Type RM Length L Ch R = 1 ,5569    ,58.4,58.4,58.4
XS GIS Cut Line= 2
2146471.05372045673753.9314837622146410.33768064673334.368080453
#Sta/Elev= 30
       0 1520.45      21 1515.69    33.1 1512.07    41.2 1508.95    61.4 1499.16
    77.6 1489.67    85.6 1483.97    97.8 1476.32   126.8 1453.98   150.3 1438.71
   162.1 1432.42   169.1 1428.02   176.2 1423.61   182.6 1422.06   198.8  1421.8
   231.1  1418.9   251.3 1418.43   257.4 1416.83   257.4 1416.82   259.4 1415.97
   271.5 1417.05   271.5 1417.06   275.6  1417.5   279.6 1419.28   295.8 1429.65
   299.8 1431.47   345.7 1448.72   376.6 1461.96   403.9  1470.4   423.9 1477.44
#Mann= 5 ,-1,0
       0      .1       0   169.1     .06       0   257.4    .045       0
   271.5     .06       0   279.6      .1       0
Bank Sta=257.4,271.5
XS Rating Curve= 0 ,0
Exp/Cntr(USF)=0,0
Exp/Cntr=0.3,0.1

Type RM Length L Ch R = 1 ,5511    ,41.4,41.4,41.4
XS GIS Cut Line= 4
2146482.19642051673768.0070893292146476.81396012 673556.29299007
2146497.83105083673404.9699370022146660.99701148673009.593855275
#Sta/Elev= 30
       0 1525.21    30.8 1522.95    58.8 1514.36    82.9 1500.45   118.9 1477.42
   138.9 1461.87   150.9 1454.12   203.7 1423.35   207.6 1422.08   251.3 1418.62
   275.5 1419.74287.4178 1416.62   295.7    1415   300.6 1416.68   307.8 1421.97
   316.8 1425.66   340.1 1431.25   377.3 1437.52   399.9 1445.72   421.3 1451.64
   433.5 1453.51   454.6 1453.17   472.5 1456.82   531.6    1489   589.8 1511.96
   636.9 1533.87   662.9 1544.55   714.8 1563.26   771.1 1574.22   792.3 1575.79
#Mann= 4 ,-1,0
       0      .1       0     200     .06       0287.4178    .045       0
   300.6      .1       0
Bank Sta=287.4178,300.6
XS Rating Curve= 0 ,0
Exp/Cntr(USF)=0,0
Exp/Cntr=0.3,0.1

Type RM Length L Ch R = 1 ,5469    ,37.8,37.8,37.8
XS GIS Cut Line= 4
2146542.82908728673756.8543361152146521.33352402673551.445364066
2146541.65004504673412.7325654212146721.62967825 672998.44110206
#Sta/Elev= 30
       0 1537.44    27.8 1536.33    39.9 1533.27      56    1524   100.2 1492.49
   136.4 1468.49   200.8  1433.3     211 1425.14   216.9 1422.21     229 1421.79
   241.2 1419.26   269.5 1416.44   276.9 1414.47   281.6    1414   288.6 1414.48
   297.8 1416.13   305.8 1419.42   313.9 1418.71   359.3 1429.63   381.1 1437.61
   411.7 1443.56   429.1 1454.78   450.9  1463.3   498.9 1475.36   533.8 1485.56
   594.8    1512   703.4 1555.41   721.3 1559.51   756.2  1562.7   798.4 1572.43
#Mann= 5 ,-1,0
       0      .1       0     211     .06       0   276.9    .045       0
   288.6     .06       0   313.9      .1       0
Bank Sta=276.9,288.6
XS Rating Curve= 0 ,0
Exp/Cntr(USF)=0,0
Exp/Cntr=0.3,0.1

Type RM Length L Ch R = 1 ,5431    ,411.2,411.2,411.2
XS GIS Cut Line= 3
2146615.05971231673732.135982291 2146559.0141371673416.879621735
2146607.27560464673292.333899046
#Sta/Elev= 30
       0 1540.21     7.1 1537.65    27.4 1528.61    47.7  1517.4   104.6 1482.54
   116.8 1473.01   120.8 1470.59   129.2 1466.96   165.5 1443.85   185.8 1432.68
   201.7 1425.74   206.1 1423.09   210.2 1422.22   222.4 1422.12   234.6 1418.67
     250 1417.72  264.77 1414.59   271.1 1413.79   284.4 1414.71   295.5 1418.88
   303.6 1421.12   324.2 1424.18     337 1427.57   349.9 1433.31   367.1 1442.66
   401.4 1448.41   405.7 1450.45   413.6  1455.8   422.8 1461.01   453.8 1469.15
#Mann= 5 ,-1,0
       0      .1       0   201.7     .06       0  264.77    .045       0
   284.4     .06       0   303.6      .1       0
Bank Sta=264.77,284.4
XS Rating Curve= 0 ,0
Exp/Cntr(USF)=0,0
Exp/Cntr=0.3,0.1

Type RM Length L Ch R = 1 ,5019    ,320.5,329,337.7
XS GIS Cut Line= 3
2146847.71790309673769.227315131 2147009.4166389673527.278095618
2146814.18038751672960.733636066
#Sta/Elev= 30
       0 1550.18    36.8 1546.43    72.8 1537.86   124.4 1512.13   170.5 1481.15
   211.7 1457.05   250.2 1437.87   283.9  1425.9   310.2  1420.8   394.3 1417.49
   403.2 1415.28   416.4 1416.01   466.7 1414.59   479.3 1409.28   487.8 1407.25
  499.351409.265   513.2  1410.4   517.5 1411.93   542.8 1432.23   580.9 1450.85
   606.3 1460.83   640.2 1471.44   660.4 1479.61   690.1 1492.41   715.3  1506.2
     731 1508.94   745.9 1519.56   805.2 1548.86     839 1557.71   890.2 1563.95
#Mann= 7 ,-1,0
       0      .1       0  341.01     .08       0  371.01      .1       0
  441.01     .06       0   479.3    .045       0  499.35     .06       0
  551.01      .1       0
Bank Sta=479.3,499.35
XS Rating Curve= 0 ,0
Exp/Cntr(USF)=0,0
Exp/Cntr=0.3,0.1

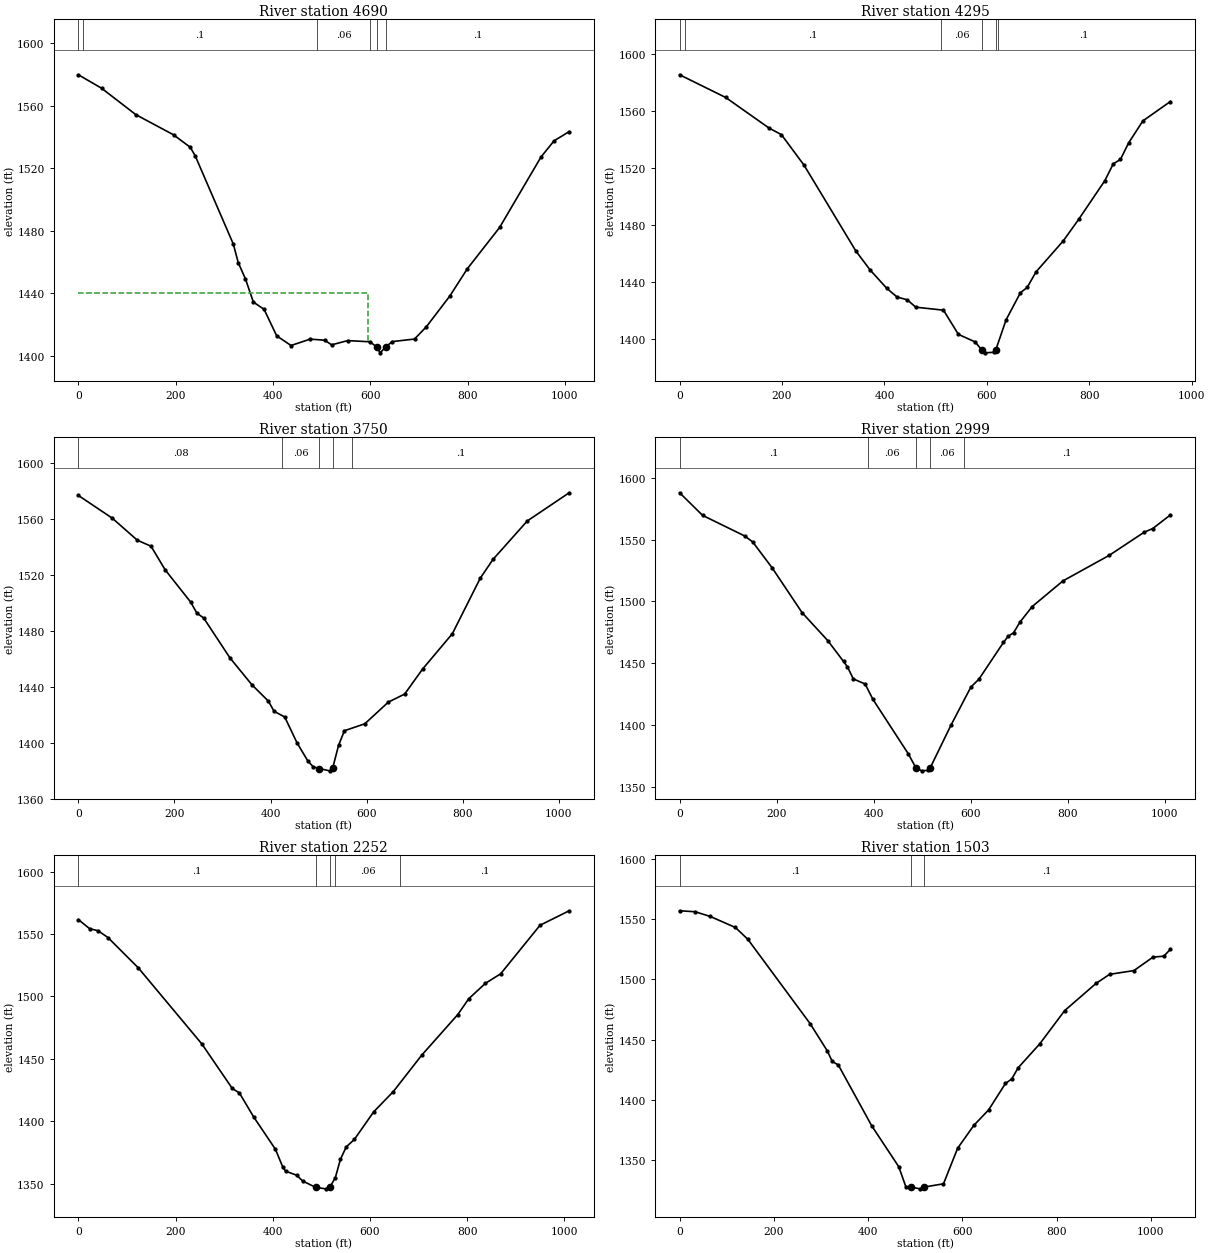
Type RM Length L Ch R = 1 ,4690    ,383.7,394.2,398.4
XS GIS Cut Line= 4
2147522.06151985673780.0072308522147219.02611125673358.392749325
2147265.73907937673191.9029398582147064.51398592672947.558183518
#Sta/Elev= 30
       0  1579.7    47.8 1571.06     118  1554.2   195.6 1541.27   229.8 1533.34
   239.9 1527.97   318.5 1471.29   328.6  1459.4   343.4 1449.05   359.6 1434.26
   381.7 1429.57   407.5 1412.66     437 1406.45   476.3 1410.53   505.9 1409.87
   520.5 1406.88   553.6 1409.59   599.4 1408.83  613.191405.446   620.2 1401.76
   631.4 1405.45   645.1 1408.96   690.8 1410.58   715.1 1418.42   763.4 1438.11
   799.3 1455.54   865.7 1481.98   950.9 1527.14   977.7 1537.46  1008.7 1543.33
#Mann= 6 ,-1,0
       0     .08       0      10      .1       0     490     .06       0
  599.22      .1       0  613.19    .045       0   631.4      .1       0
#XS Ineff= 2 , 0
          594.39 1440.34
Permanent Ineff=
       F       F
Bank Sta=613.19,631.4
XS Rating Curve= 0 ,0
Exp/Cntr(USF)=0,0
Exp/Cntr=0.3,0.1

Type RM Length L Ch R = 1 ,4295    ,536,545.9,548.7
XS GIS Cut Line= 3
2147559.19234067673782.4027676782147501.69945682673324.855233748
2147755.62636047672897.251910154
#Sta/Elev= 30
       0 1585.24    89.9 1569.36   174.6 1547.94   198.8 1543.33   243.1 1521.89
     344 1461.96   372.1 1448.55   404.4 1435.79   424.5 1429.67   444.7 1427.66
   461.1 1422.53   515.3 1420.43   544.4 1403.51   577.1 1398.21   590.6 1392.38
   595.7 1390.56   614.3 1390.98   617.4 1392.54   637.5 1413.63   665.5 1432.59
   678.7 1436.33   696.2  1447.3   749.2 1468.94   779.4 1484.04   830.5 1511.16
   846.9  1522.9   860.9 1525.95   876.9 1537.54   904.7 1552.94   958.5 1566.53
#Mann= 6 ,-1,0
       0     .08       0      10      .1       0  511.15     .06       0
   590.6    .045       0   617.4     .06       0  621.15      .1       0
Bank Sta=590.6,617.4
XS Rating Curve= 0 ,0
Exp/Cntr(USF)=0,0
Exp/Cntr=0.3,0.1

Type RM Length L Ch R = 1 ,3750    ,764.2,750.6,737
XS GIS Cut Line= 6
2147752.30447201673827.2918425052147922.58562751673574.194251582
2147976.19149143673502.3118494152148028.24092801673447.723047838
2148229.24216643 673278.966167512148448.03930101673090.154209167
#Sta/Elev= 30
       0 1577.09    70.7 1560.78   122.6 1545.06   151.2 1540.73   180.6 1523.84
   233.7 1500.75   246.5  1492.9   260.9 1489.29   315.5 1460.77   361.2 1441.53
   395.5 1429.81   407.3 1422.56   429.5 1418.47   454.9 1400.09   477.6 1386.95
   488.9 1382.78   501.7 1381.56   522.8 1379.91   529.2 1381.72   541.5  1398.1
   553.7 1408.62   596.2 1413.59   645.2 1429.13   679.1 1434.87   716.6 1452.85
   778.4 1478.09   836.6 1517.91     863 1531.29   934.5 1558.87  1021.6 1579.01
#Mann= 5 ,-1,0
       0     .08       0  424.72     .06       0   501.7    .045       0
   529.2     .06       0  570.15      .1       0
Bank Sta=501.7,529.2
XS Rating Curve= 0 ,0
Exp/Cntr(USF)=0,0
Exp/Cntr=0.3,0.1

Type RM Length L Ch R = 1 ,2999    ,722.7,746.8,753.5
XS GIS Cut Line= 6
2148598.03572017674250.7535940112148646.43424542674060.619131759
2148677.42565326673881.323886678 2148694.1178771673704.875092596
2148711.94822201673630.9874450862148858.03946526673280.144314751
#Sta/Elev= 30
       0 1587.71    47.4 1569.47   134.2 1552.84   150.6 1548.05   190.6 1527.21
   252.6 1490.91   305.4 1468.42   337.9 1451.59   345.9 1447.27   358.1  1437.5
   382.4 1433.38   398.5 1420.97   471.1 1377.24   487.1 1365.74   499.1  1363.3
   511.1 1363.69  516.741365.849   559.3 1400.07   600.5 1430.95     617 1437.25
   667.6 1466.96     677 1471.74   688.6 1474.79   701.3 1483.15   726.9 1495.91
   790.2 1516.56   885.8 1537.25   957.8 1555.89   975.4 1558.86  1011.8 1569.85
#Mann= 5 ,-1,0
       0      .1       0  388.24     .06       0   487.1    .045       0
  516.74     .06       0  585.54      .1       0
Bank Sta=487.1,516.74
XS Rating Curve= 0 ,0
Exp/Cntr(USF)=0,0
Exp/Cntr=0.3,0.1

Type RM Length L Ch R = 1 ,2252    ,745,749.6,741.4
XS GIS Cut Line= 6
 2148824.8774581674478.0267615022149068.90945034 674316.10549742
2149201.28845067674218.5528710042149325.85709918674095.549180001
2149390.84253351674036.8567120882149615.41459093673853.967970252
#Sta/Elev= 30
       0 1561.58      23 1554.34    40.6 1552.66    60.9 1547.19   123.2 1522.96
   254.2  1461.9   316.5 1426.39   331.2 1422.77   360.3 1403.72   405.4 1377.62
   420.4 1363.48   426.2 1360.12     449 1356.88   461.4 1352.24   487.9 1347.18
   508.5 1345.96   517.5 1347.39   528.7 1355.02   539.2 1369.71   551.1 1379.56
   567.7  1385.5   607.5 1407.62   647.9 1423.86   706.5 1453.09   780.3 1485.42
     803 1498.15   837.2  1510.5   868.7 1518.16   949.8 1557.08  1009.7 1568.65
#Mann= 5 ,-1,0
       0      .1       0   487.9    .045       0   517.5      .1       0
  527.36     .06       0  662.42      .1       0
Bank Sta=487.9,517.5
XS Rating Curve= 0 ,0
Exp/Cntr(USF)=0,0
Exp/Cntr=0.3,0.1

Type RM Length L Ch R = 1 ,1503    ,757.9,749.3,735.7
XS GIS Cut Line= 6
 2149403.2896871675031.3471771782149522.37311034674876.147028252
2149748.59870775674600.1226459292149776.47627668 674527.57554692
2149820.63202825674441.6977659172149993.74191825674178.878737763
#Sta/Elev= 30
       0 1556.89    32.8  1556.1      65 1552.18   118.3 1543.05   144.9 1533.17
     277 1463.22   313.4 1440.66   323.9 1431.87   336.7 1429.01   407.7 1378.48
   465.1 1344.52   480.2 1327.82   491.7 1327.54   510.7  1326.2  518.391327.657
     560 1330.37     590 1359.86   624.3  1378.8   655.9 1391.76   691.5 1413.62
   704.9 1417.37   718.4 1426.62   764.2 1446.43     817 1473.99   883.7 1496.61
   912.6 1504.18   964.1 1507.27  1004.8 1518.48  1027.4  1519.2  1041.6 1524.92
#Mann= 3 ,-1,0
       0      .1       0   491.7    .045       0  518.39      .1       0
Bank Sta=491.7,518.39
XS Rating Curve= 0 ,0
Exp/Cntr(USF)=0,0
Exp/Cntr=0.3,0.1

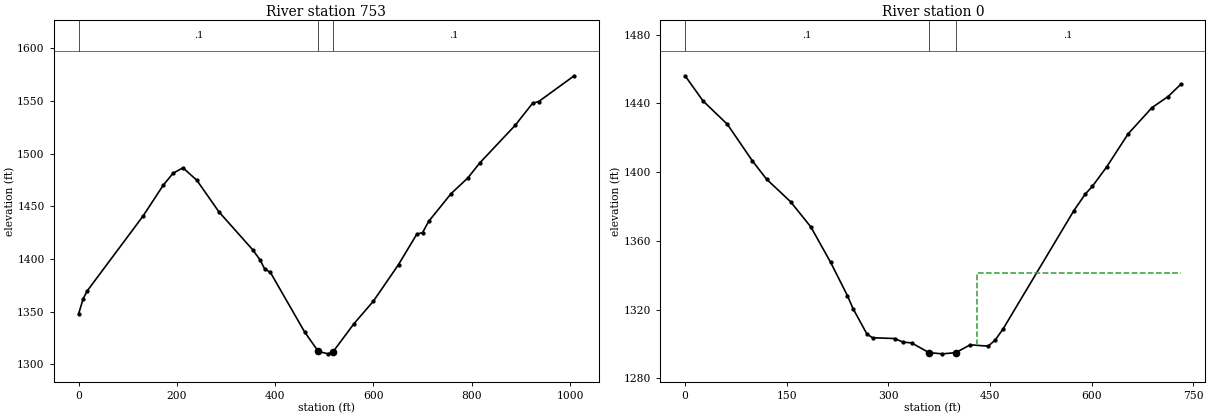
Type RM Length L Ch R = 1 ,753     ,659.1,753.3,687.8
XS GIS Cut Line= 6
2150319.69730309675378.497401506 2150335.4157756675280.863082334
2150395.92549708674928.7230385842150404.27456176674828.631047174
2150414.88313635674475.6652176682150426.80174768674377.673943833
#Sta/Elev= 30
       0 1348.03     9.4 1362.46    17.5 1369.76   131.1 1440.77   171.9 1469.83
     192 1481.33   212.3 1486.57   240.7 1474.65   285.3 1444.89   354.3 1408.73
   369.3  1399.1   378.6  1390.5   390.1  1387.4   459.7 1330.94   487.8 1312.27
     508    1310  518.121312.148   560.1 1338.45   600.1 1360.13   651.1 1394.77
   688.1  1423.5   700.1 1425.14   712.2  1435.6     758 1462.05   792.2 1476.99
   816.2 1491.09   888.2 1526.76   923.9 1547.82   936.4 1549.45  1008.5 1573.89
#Mann= 3 ,-1,0
       0      .1       0   487.8    .045       0  518.12      .1       0
Bank Sta=487.8,518.12
XS Rating Curve= 0 ,0
Exp/Cntr(USF)=0,0
Exp/Cntr=0.3,0.1

Type RM Length L Ch R = 1 ,0       ,844.8,844.8,844.8
XS GIS Cut Line= 4
2150675.49997512 675264.53581144 2150999.6589054675185.716345517
2151072.92770471675204.5886120052151283.85303606675447.707809714
#Sta/Elev= 30
       0 1456.02    26.5 1441.36    62.4  1427.8    99.4 1406.45   120.1 1395.94
   155.7 1382.74   185.5 1368.13   214.8 1347.45   239.5 1328.14   247.7 1320.67
   268.3 1305.81   276.5 1303.68   309.4 1303.21   321.2 1301.15   334.1 1300.67
   359.9    1295   379.6 1294.31   399.3 1294.98   420.6 1299.56   447.1 1298.78
   457.4 1302.27   469.2 1308.84   573.6 1377.61   590.1 1387.08   600.7 1391.65
   621.8 1402.91   653.6 1422.23   688.9 1437.52   712.6 1443.96   731.1 1450.97
#Mann= 3 ,-1,0
       0      .1       0   359.9    .045       0   399.3      .1       0
#XS Ineff= 2 , 0
                          431.34         1341.14
Permanent Ineff=
       F       F
Bank Sta=359.9,399.3
XS Rating Curve= 0 ,0
Exp/Cntr=0.3,0.1
LCMann Table=0

Chan Stop Cuts=-1
Use User Specified Reach Order=0
Composite Channel Slope=5